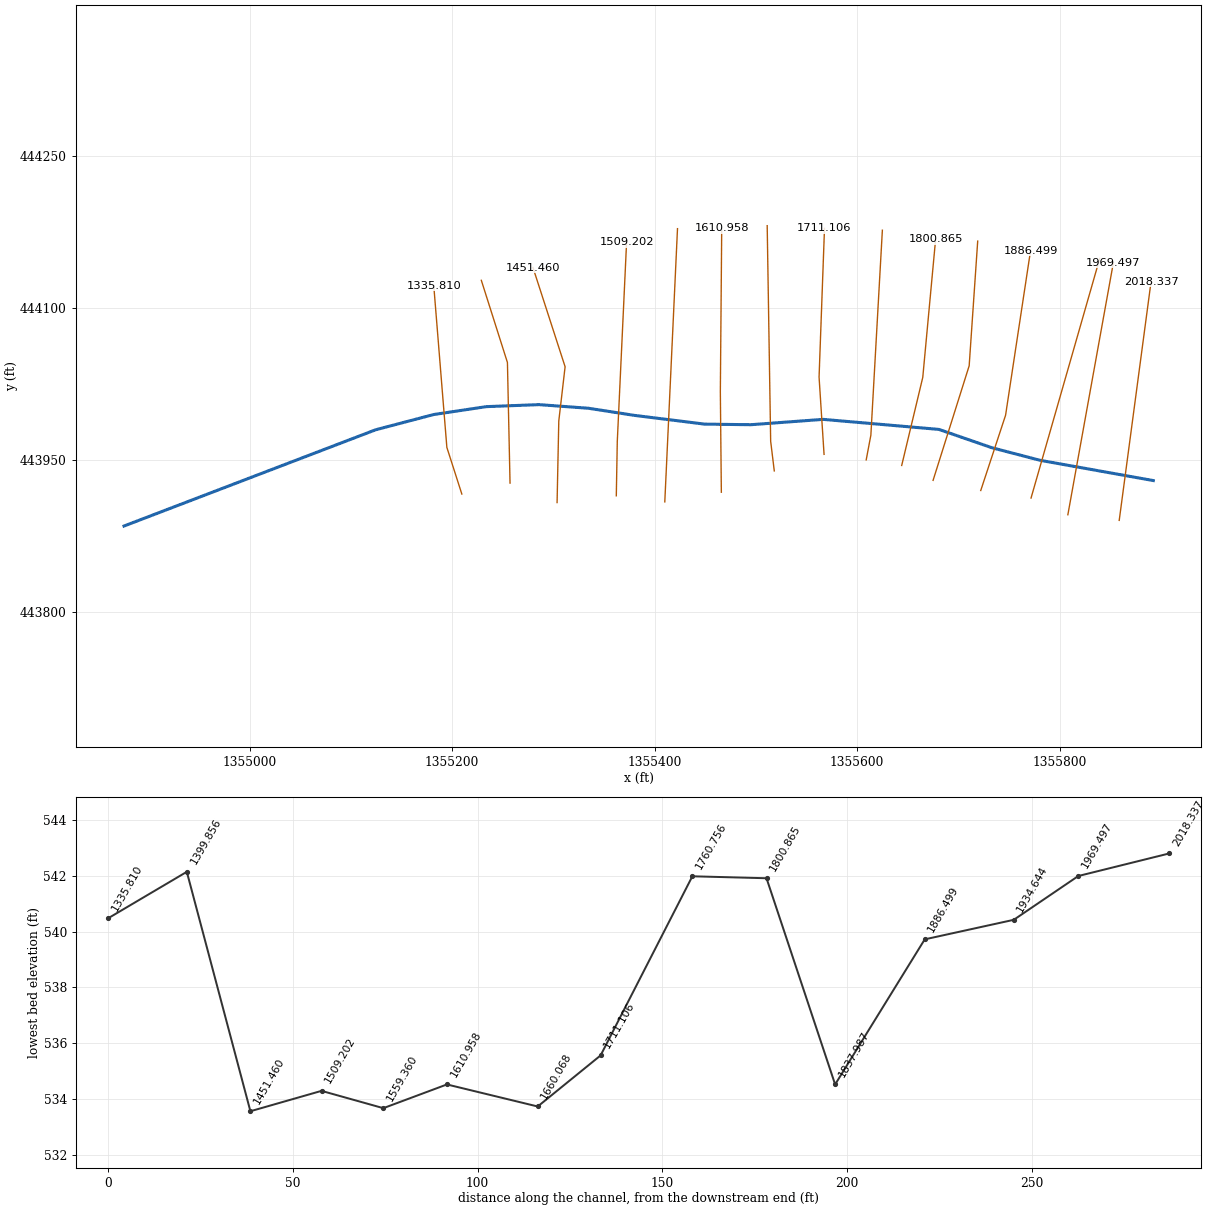
--- TaylorCreek.prj (project) ---

Proj Title=Taylor Creek
Current Plan=p01
Default Exp/Contr=0.3,0.1
English Units
Geom File=g01
Flow File=f01
Plan File=p01
Y Axis Title=Elevation
X Axis Title(PF)=Main Channel Distance
X Axis Title(XS)=Station
BEGIN DESCRIPTION:
Existing Conditions Tayler Creek at Sheed Road
HAM-74-11.25 PID 113464
END DESCRIPTION:
DSS Export Rating Curves= 0
DSS Export Rating Curve Sorted= 0
DSS Export Volume Flow Curves= 0
DXF OffsetX= 0
DXF OffsetY= 0
DXF ScaleX= 1
DXF ScaleY= 10

--- TaylorCreek.p01 (plan) ---

Plan Title=Existing
Program Version=5.07
Short Identifier=Existing
Geom File=g01
Flow File=f01
Mixed Flow
K Sum by GR= 0
Std Step Tol= 0.01
Critical Tol= 0.01
Num of Std Step Trials= 20
Max Error Tol= 0.3
Flow Tol Ratio= 0.001
Split Flow NTrial= 30
Split Flow Tol= 0.02
Split Flow Ratio= 0.02
Log Output Level= 0
Friction Slope Method= 1
Unsteady Friction Slope Method= 2
Unsteady Bridges Friction Slope Method= 1
Parabolic Critical Depth
Global Vel Dist= 5 , 5 , 5
Global Log Level= 0
CheckData=True
Encroach Param=-1 ,0,0, 0
Computation Interval=1MIN
Output Interval=1HOUR
Instantaneous Interval=1HOUR
Mapping Interval=1HOUR
Computation Time Step Use Courant=        0
Computation Time Step Use Time Series=    0
Computation Time Step Count To Double=0
Computation Time Step Max Doubling=0
Computation Time Step Max Halving=0
Computation Time Step Residence Courant=0
Run HTab= 0
Run UNet= 0
Run Sediment= 0
Run PostProcess= 0
Run WQNet= 0
Run RASMapper= 0
UNET Theta= 1
UNET Theta Warmup= 1
UNET ZTol= 0.02
UNET ZSATol= 0.02
UNET MxIter= 20
UNET Max Iter WO Improvement= 0
UNET MaxInSteps= 0
UNET DtIC= 0
UNET DtMin= 0
UNET MaxCRTS= 20
UNET WFStab= 2
UNET SFStab= 1
UNET WFX= 1
UNET SFX= 1
UNET 1D Methodology=Finite Difference
UNET DSS MLevel= 4
UNET Pardiso=0
UNET DZMax Abort= 100
UNET Use Existing IB Tables=-1
UNET Froude Reduction=False
UNET Froude Limit= 0.8
UNET Froude Power= 4
UNET D1 Cores= 0
UNET D2 Coriolis=0
UNET D2 Cores= 0
UNET D2 Theta= 1
UNET D2 Theta Warmup= 1
UNET D2 Z Tol= 0.01
UNET D2 Volume Tol= 0.01
UNET D2 Max Iterations= 20
UNET D2 Equation= 0
UNET D2 RampUpFraction=0.1
UNET D2 TimeSlices= 1
UNET D2 BCVolumeCheck=0
UNET D1D2 MaxIter= 0
UNET D1D2 ZTol=0.01
UNET D1D2 QTol=0.1
UNET D1D2 MinQTol=1
Write IC File= 0
Write IC File at Fixed DateTime=0
Write IC File at Sim End=0
Echo Input=False
Echo Parameters=False
Echo Output=False
Write Detailed= 0
HDF Write Warmup=0
HDF Write Time Slices=0
HDF Flush=0
HDF Face Node Velocities=0
HDF Compression= 1
HDF Chunk Size= 1
HDF Spatial Parts= 1
HDF Use Max Rows=0
HDF Fixed Rows= 1
Calibration Method= 0
Calibration Iterations= 20
Calibration Max Change=0.05
Calibration Tolerance=0.2
Calibration Maximum=1.5
Calibration Minimum=0.5
Calibration Optimization Method= 1
WQ AD Non Conservative
WQ ULTIMATE=-1
WQ Max Comp Step=1HOUR
WQ Output Interval=15MIN
WQ Output Selected Increments= 0
WQ Output face flow=0
WQ Output face velocity=0
WQ Output face area=0
WQ Output face dispersion=0
WQ Output cell volume=0
WQ Output cell surface area=0
WQ Output cell continuity=0
WQ Output cumulative cell continuity=0
WQ Output face conc=0
WQ Output face dconc_dx=0
WQ Output face courant=0
WQ Output face peclet=0
WQ Output face adv mass=0
WQ Output face disp mass=0
WQ Output cell mass=0
WQ Output cell source sink temp=0
WQ Output nsm pathways=0
WQ Output nsm derived pathways=0
WQ Output MaxMinRange=-1
WQ Daily Max Min Mean=-1
WQ Daily Range=0
WQ Daily Time=0
WQ Create Restart=0
WQ Fixed Restart=0
WQ System Summary=0
WQ Write To DSS=0
WQ Use Fixed Temperature=0
Sorting and Armoring Iterations= 10
XS Update Threshold= 0.02
Bed Roughness Predictor= 0
Hydraulics Update Threshold= 0.02
Energy Slope Method= 1
Volume Change Method= 1
Sediment Retention Method= 0
XS Weighting Method= 0
Number of US Weighted Cross Sections= 1
Number of DS Weighted Cross Sections= 1
Upstream XS Weight=0
Main XS Weight=1
Downstream XS Weight=0
Number of DS XS's Weighted with US Boundary= 1
Upstream Boundary Weight= 1
Weight of XSs Associated with US Boundary= 0
Number of US XS's Weighted with DS Boundary= 1
Downstream Boundary Weight= 0.5
Weight of XSs Associated with DS Boundary= 0.5
Percentile Method= 0
Sediment Output Level= 3
Mass or Volume Output= 0
Output Increment Type= 1
Profile and TS Output Increment= 1
XS Output Flag= 0
XS Output Increment= 10
Write Gradation File= 0
Read Gradation Hotstart= 0
Write HDF5 File= 1
Write Binary Output= 1
Write DSS Sediment File= 0
SV Curve= 0
Specific Gage Flag= 0

--- TaylorCreek.f01 (steady flow) ---

Flow Title=StreamStatsFlows
Program Version=5.07
Number of Profiles= 8
Profile Names=2yr,5yr,10yr,25yr,50yr,100yr,500yr,STD
River Rch & RM=Taylor Creek,Reach           ,2018.337
    1270    2100    2740    3640    4360    5130    7120      54
Boundary for River Rch & Prof#=Taylor Creek,Reach           , 1
Up Type= 3
Up Slope=0.007
Dn Type= 3
Dn Slope=0.01
Boundary for River Rch & Prof#=Taylor Creek,Reach           , 2
Up Type= 3
Up Slope=0.007
Dn Type= 3
Dn Slope=0.01
Boundary for River Rch & Prof#=Taylor Creek,Reach           , 3
Up Type= 3
Up Slope=0.007
Dn Type= 3
Dn Slope=0.01
Boundary for River Rch & Prof#=Taylor Creek,Reach           , 4
Up Type= 3
Up Slope=0.007
Dn Type= 3
Dn Slope=0.01
Boundary for River Rch & Prof#=Taylor Creek,Reach           , 5
Up Type= 3
Up Slope=0.007
Dn Type= 3
Dn Slope=0.01
Boundary for River Rch & Prof#=Taylor Creek,Reach           , 6
Up Type= 3
Up Slope=0.007
Dn Type= 3
Dn Slope=0.01
Boundary for River Rch & Prof#=Taylor Creek,Reach           , 7
Up Type= 3
Up Slope=0.007
Dn Type= 3
Dn Slope=0.01
DSS Import GetInterval= 0
DSS Import GetPeak= 0
DSS Import FillOption= 0

--- TaylorCreek.g01 (geometry) ---

Geom Title=Existing Conditions
Program Version=5.07

River Reach=Taylor Creek    ,Reach
Reach XY= 22
1355892.48073077 443929.612590251355780.66827761 443949.62282646
1355780.66827761 443949.622826461355733.13932115 443962.01920915
1355680.80892721 443980.129774931355680.80892721 443980.12977493
1355566.46433013  443990.04368271355566.46433013  443990.0436827
1355494.95003702 443984.763246521355494.95003702 443984.76324652
1355449.48416915 443985.345262141355449.48416915 443985.34526214
1355380.23413168 443993.962249181355380.23413167 443993.96224918
1355334.71667924 444001.022958321355285.88624513 444004.59372636
1355285.88624513 444004.593726361355233.88861859 444002.61975876
 1355181.8573638 443994.81534451 1355181.8573638 443994.81534451
 1355124.4035045 443979.709164751354876.05868254 443884.71690857

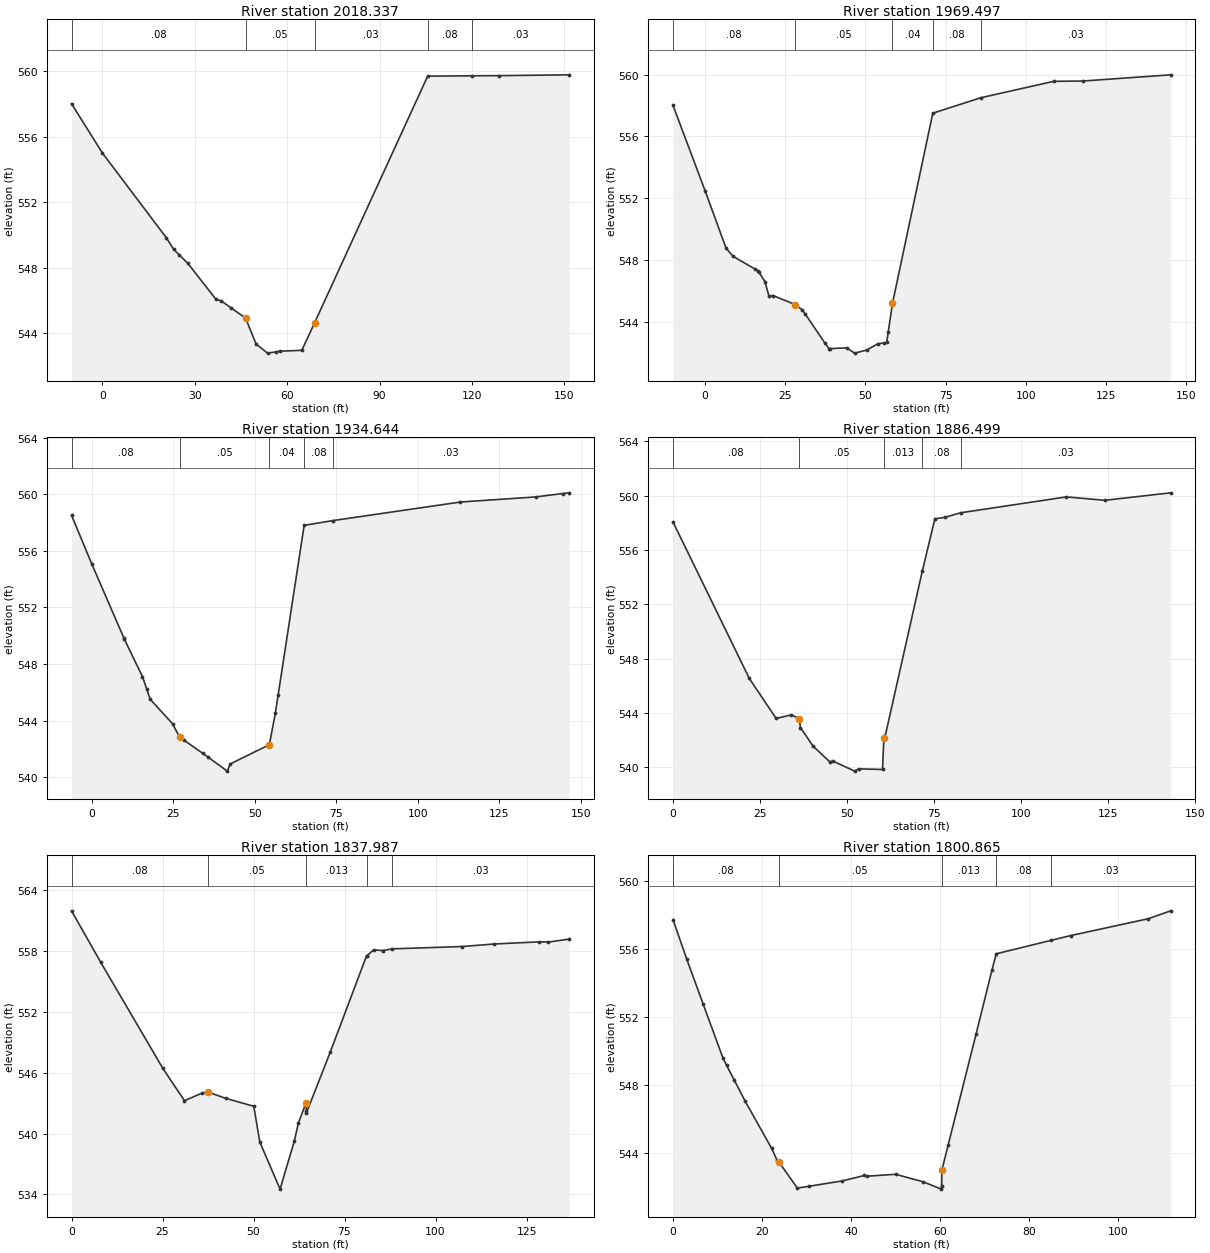
Type RM Length L Ch R = 1 ,2018.337,24.64,24.64,24.64
XS GIS Cut Line= 2
 1355858.8330802 443890.294081341355890.28056321 444126.03824269
#Sta/Elev= 20
     -10     558       0     555   20.82  549.82   23.12  549.13   24.83  548.81
   27.71  548.28   36.88  546.08   38.52  545.99   41.91  545.54   46.47  544.94
   49.92  543.35   53.62   542.8   56.39  542.88   57.68  542.92   64.75  542.97
    68.9  544.65   105.6  559.68     120   559.7  128.76  559.71  151.51  559.76
#Mann= 5 ,-1 , 0
     -10     .08       0   46.47     .05       0    68.9     .03       0
   105.6     .08       0     120     .03       0
Bank Sta=46.47,68.9
XS Rating Curve= 0 ,0
Exp/Cntr=0.3,0.1

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
Type RM Length L Ch R = 1 ,1969.497,18,17.46,17
XS GIS Cut Line= 2
1355808.11753546 443895.846276281355853.02982258 444144.58127772
#Sta/Elev= 29
     -10     558       0  552.48    6.54  548.77    8.63  548.26   15.67  547.41
   16.55   547.3   16.77  547.23   18.66  546.61   19.93  545.66   21.19  545.71
    28.1  545.13   30.34  544.78   31.14  544.54   37.26  542.67   38.68  542.27
   38.84  542.28   44.16  542.33    46.6  541.99   50.44  542.19    53.8  542.59
   55.75  542.65   56.62  542.68   57.12  543.38   58.43  545.21      71   557.5
      86   558.5   108.7  559.56  117.83  559.58  145.15  559.98
#Mann= 5 ,-1 , 0
     -10     .08       0    28.1     .05       0   58.43     .04       0
      71     .08       0      86     .03       0
Bank Sta=28.1,58.43
XS Rating Curve= 0 ,0
Exp/Cntr=0.3,0.1

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
Type RM Length L Ch R = 1 ,1934.644,24.58,24.08,23.66
XS GIS Cut Line= 2
1355771.75685369 443912.353511921355839.58347394 444148.91415952
#Sta/Elev= 23
   -6.23  558.51       0  555.06    9.87  549.81      10  549.74   15.54   547.1
   16.81  546.24   17.88  545.51   24.76  543.77    26.9  542.84   28.27  542.61
   34.03  541.68   35.79  541.39   41.56  540.42   42.48  540.93   54.47  542.29
    56.3   544.5   57.18  545.82   65.15   557.8   74.06  558.14  113.11  559.45
  136.22  559.81  144.51  560.05  146.45   560.1
#Mann= 5 ,-1 , 0
   -6.23     .08       0    26.9     .05       0   54.47     .04       0
   65.15     .08       0   74.06     .03       0
Bank Sta=26.9,54.47
XS Rating Curve= 0 ,0
Exp/Cntr=0.3,0.1

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
Type RM Length L Ch R = 1 ,1886.499,24.12,24.24,24.4
XS GIS Cut Line= 3
1355722.08796983 443919.776545791355746.61617712 443994.13232381
 1355771.2614567 444156.57232426
#Sta/Elev= 22
       0  558.06    21.9  546.55   29.62   543.6   33.99  543.86   36.23  543.59
   36.61  542.93   40.23  541.56   45.05   540.4   45.92  540.46   52.22  539.72
    53.3  539.89   60.19  539.84    60.6  542.28   60.71  542.18   60.74  542.06
   71.65  554.48   75.23   558.3   78.07   558.4   82.61  558.74  113.01  559.91
  124.08  559.66  142.96  560.21
#Mann= 5 ,-1 , 0
       0     .08       0   36.23     .05       0    60.6    .013       0
   71.65     .08       0   82.61     .03       0
Bank Sta=36.23,60.71
XS Rating Curve= 0 ,0
Exp/Cntr=0.3,0.1

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
Type RM Length L Ch R = 1 ,1837.987,17.53,18.56,19.2
XS GIS Cut Line= 3
1355675.02633649 443929.829910241355710.66133765 444042.93919129
1355719.09098209 444166.09716571
#Sta/Elev= 26
       0  561.96    8.04  556.87   25.09  546.42   31.03  543.24   35.85  543.99
    37.4   544.1   42.38  543.47   50.07  542.69   51.72  539.17   57.29  534.52
   61.22  539.27   62.32  541.03   64.42  543.02   64.52  542.27   64.54  542.05
   71.06  548.01   81.04  557.51   81.17  557.54   82.99  558.11    85.5  558.04
    88.1  558.21  107.29  558.44  116.11  558.69   128.5   558.9  130.98  558.88
   136.7  559.17
#Mann= 5 ,-1 , 0
       0     .08       0    37.4     .05       0   64.42    .013       0
   81.17     .08       0    88.1     .03       0
#XS Ineff= 2 , 0
Permanent Ineff=
       T       F
Bank Sta=37.4,64.42
XS Rating Curve= 0 ,0
Exp/Cntr=0.3,0.1

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
Type RM Length L Ch R = 1 ,1800.865,18.08,20.06,21.65
XS GIS Cut Line= 3
1355644.03709558  443944.52974491355664.84039685 444031.50642474
1355677.50859504 444167.67499033
#Sta/Elev= 28
       0  557.71    3.09  555.39    6.79  552.75   11.23  549.59   12.04  549.17
   13.73  548.32   16.19  547.08   22.17   544.3   23.32  543.64   23.73  543.53
   27.95  541.97   30.61  542.08   38.02  542.39   43.04  542.71   43.69  542.67
   50.04  542.78   56.23  542.34   60.32  541.91    60.4  542.11   60.45  543.03
   61.88  544.52   68.12  550.99   71.69  554.74   72.67  555.71      85   556.5
   89.43  556.78   106.9  557.77  111.87  558.23
#Mann= 5 ,-1 , 0
       0     .08       0   23.73     .05       0   60.45    .013       0
   72.67     .08       0      85     .03       0
Bank Sta=23.73,60.45
XS Rating Curve= 0 ,0
Exp/Cntr=0.3,0.1

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
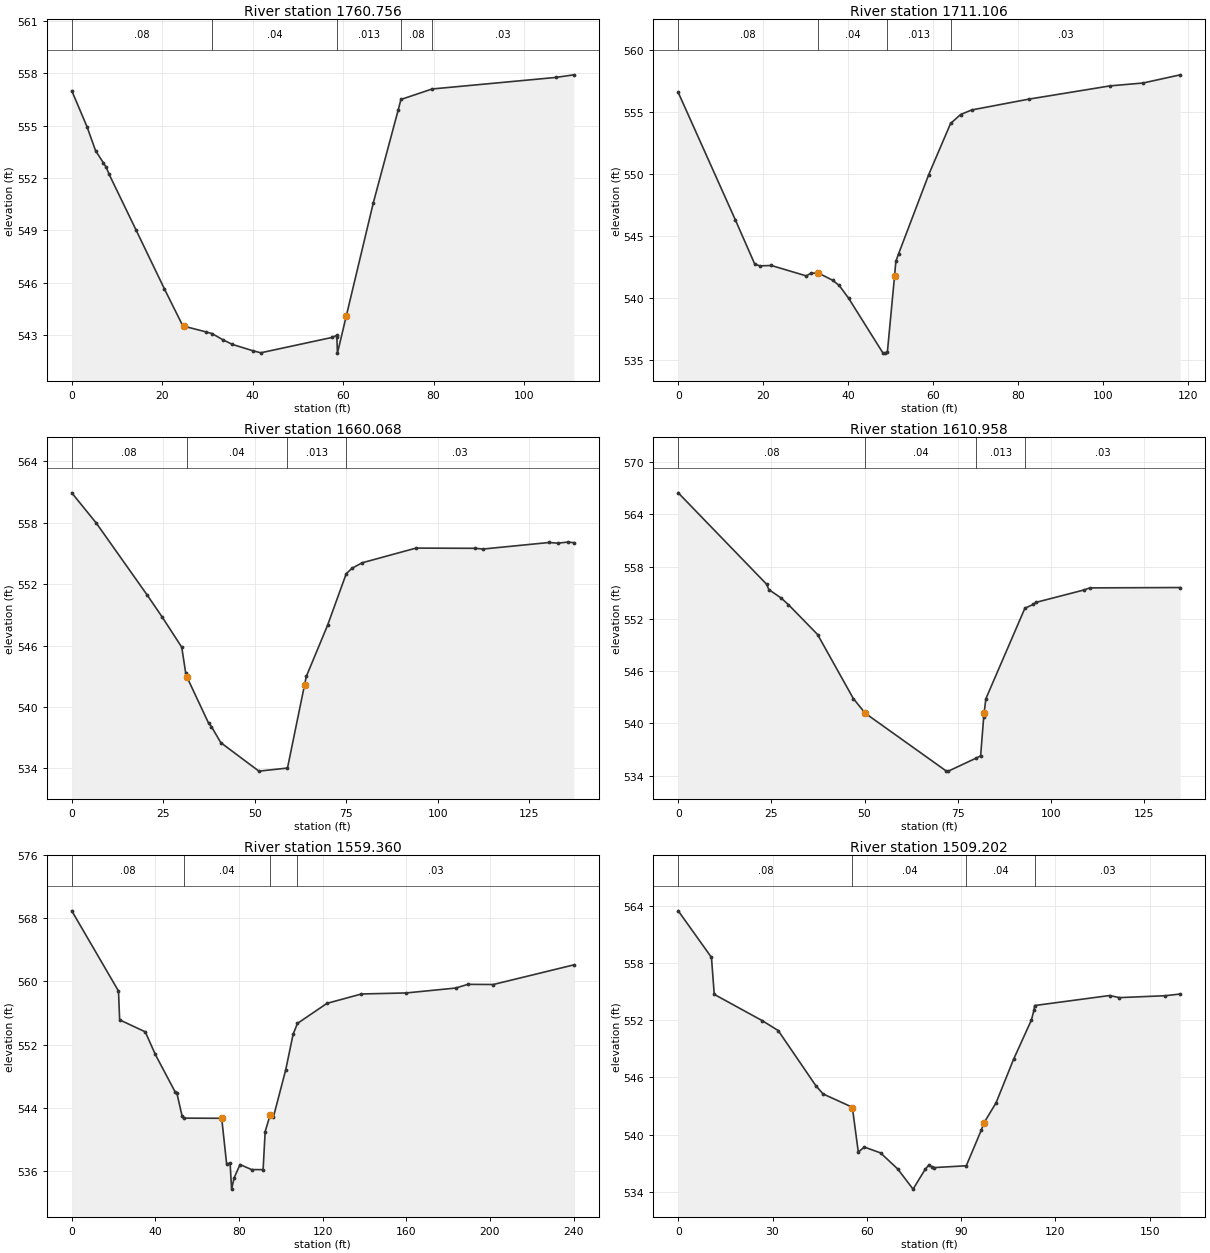
Type RM Length L Ch R = 1 ,1760.756,22.7,24.82,25.9
XS GIS Cut Line= 3
1355608.98367132 443950.060943681355613.58772793  443974.4567009
1355624.94574077 444176.83412039
#Sta/Elev= 27
       0     557    3.37  554.94    5.26  553.57    6.95  552.89    7.64  552.61
    8.27  552.21   14.25  549.01    20.5  545.65   24.56  543.54   24.83  543.52
   29.63   543.2   31.01   543.1   33.39  542.75   35.51  542.48   40.13  542.11
   41.81     542   57.59  542.88    58.6     543   58.62  542.91   58.75  541.98
   60.71  544.11    66.7   550.6   72.16  555.87   72.79   556.5    79.7   557.1
     107  557.76  111.03  557.91
#Mann= 5 ,-1 , 0
       0     .08       0   31.01     .04       0    58.6    .013       0
   72.79     .08       0    79.7     .03       0
#XS Ineff= 2 , 0
Permanent Ineff=
       T       F
Bank Sta=24.83,60.71
XS Rating Curve= 0 ,0
Exp/Cntr=0.3,0.1

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
Type RM Length L Ch R = 1 ,1711.106,17.33,17.01,16.64
XS GIS Cut Line= 3
1355567.36624588 443955.501930891355562.43828264 444031.81151306
1355567.80194995 444178.65372648
#Sta/Elev= 25
       0  556.56   13.48  546.27   18.02  542.73   19.23  542.59   21.93  542.62
   30.17  541.78   31.18  541.99   32.95  542.02   36.36  541.43    37.9  541.01
    40.1  539.99   48.18  535.58   48.72  535.56   49.24  535.64   50.93  541.77
   51.24  542.96   51.88  543.56   58.96  549.93   64.12  554.06   66.47  554.78
   69.09  555.15   82.52  556.02  101.67  557.09  109.42  557.32  118.21  557.98
#Mann= 4 ,-1 , 0
       0     .08       0   32.95     .04       0   49.24    .013       0
   64.12     .03       0
Bank Sta=32.95,50.93
XS Rating Curve= 0 ,0
Exp/Cntr=0.3,0.1

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
Type RM Length L Ch R = 1 ,1660.068,24.68,24.56,24.5
XS GIS Cut Line= 3
1355518.20778962 443939.149299481355514.64095205 443968.47533939
1355511.21305503 444181.31299002
#Sta/Elev= 25
       0  560.92    6.73  557.95   20.63  550.92   24.62  548.83   30.04  545.84
   31.11  543.35    31.4  542.97   37.36  538.43   38.13  538.09   40.72  536.51
   51.12  533.73   58.93  534.03   63.58  542.14   64.07  542.98   69.88  547.98
   74.98  553.02   76.56  553.55   79.29  554.08   94.03  555.52  110.19   555.5
  112.38  555.43   130.5  556.07  132.73     556  135.51  556.11  137.16  556.05
#Mann= 4 ,-1 , 0
       0     .08       0    31.4     .04       0   58.93    .013       0
   74.98     .03       0
Bank Sta=31.4,63.58
XS Rating Curve= 0 ,0
Exp/Cntr=0.3,0.1

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
Type RM Length L Ch R = 1 ,1610.958,17.68,17.2,16.83
XS GIS Cut Line= 3
 1355465.9400756 443918.10829806 1355464.9492816 444017.27751716
1355466.31072789 444178.87087938
#Sta/Elev= 21
       0  566.46   23.72  555.97   24.33  555.35   27.58   554.4   29.55  553.64
    37.4   550.2   47.01  542.84   50.18  541.17   71.85  534.56   72.51  534.52
   80.04  536.03   81.16  536.27   81.98  540.68   82.11  541.22   82.57  542.83
   93.04  553.21    95.3  553.66   95.95  553.88  108.89  555.31   110.5  555.55
  134.76  555.59
#Mann= 4 ,-1 , 0
       0     .08       0   50.18     .04       0   80.04    .013       0
   93.04     .03       0
Bank Sta=50.18,82.11
XS Rating Curve= 0 ,0
Exp/Cntr=0.3,0.1

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
Type RM Length L Ch R = 1 ,1559.360,16.52,16.72,16.63
XS GIS Cut Line= 2
1355410.09598047 443908.571511121355422.63720399 444178.37987375
#Sta/Elev= 30
       0  568.95   22.35  558.78    22.9  555.13   35.16  553.61   39.97  550.74
   49.53  545.95   50.29  545.82   52.71     543   53.46  542.67   71.72  542.65
   74.05  536.91   75.74  536.94   76.45  533.67   77.67  535.11    80.5  536.79
   85.97  536.15   91.52  536.14    92.5  540.97   94.85  543.04   96.45  542.82
  102.33  548.79  105.87   553.3  107.95  554.68  122.06  557.22  138.58  558.41
  159.96  558.54  183.59  559.16  189.48  559.63  201.62  559.61  240.15   562.1
#Mann= 4 ,-1 , 0
       0     .08       0   53.46     .04       0   94.85    .013       0
  107.95     .03       0
#XS Ineff= 2 , 0
Permanent Ineff=
       T       F
Bank Sta=71.72,94.85
XS Rating Curve= 0 ,0
Exp/Cntr=0.3,0.1

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
Type RM Length L Ch R = 1 ,1509.202,19.4,19.24,18.8
XS GIS Cut Line= 3
1355362.21057756  443914.60042411355363.18227763 443968.23112315
1355372.37030666 444165.07989103
#Sta/Elev= 30
       0  563.47   10.57  558.59   11.46  554.71   26.75  551.95    31.8  550.92
   43.79  545.13   46.09  544.27   55.09  542.92   55.44  542.77   57.29  538.17
   59.21   538.7   64.36  538.09   69.82  536.41   74.72  534.29   78.57  536.37
   79.85  536.86   80.65  536.61   81.52  536.55   91.65  536.74   96.44  540.49
   97.21   541.2  101.14  543.35  106.68  547.89  112.38  552.03  113.21  553.08
  113.41  553.54  137.24  554.59   140.4  554.37  154.99  554.57  159.75  554.75
#Mann= 4 ,-1 , 0
       0     .08       0   55.44     .04       0   91.65     .04       0
  113.41     .03       0
#XS Ineff= 2 , 0
Permanent Ineff=
       T       F
Bank Sta=55.44,97.21
XS Rating Curve= 0 ,0
Exp/Cntr=0.3,0.1

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
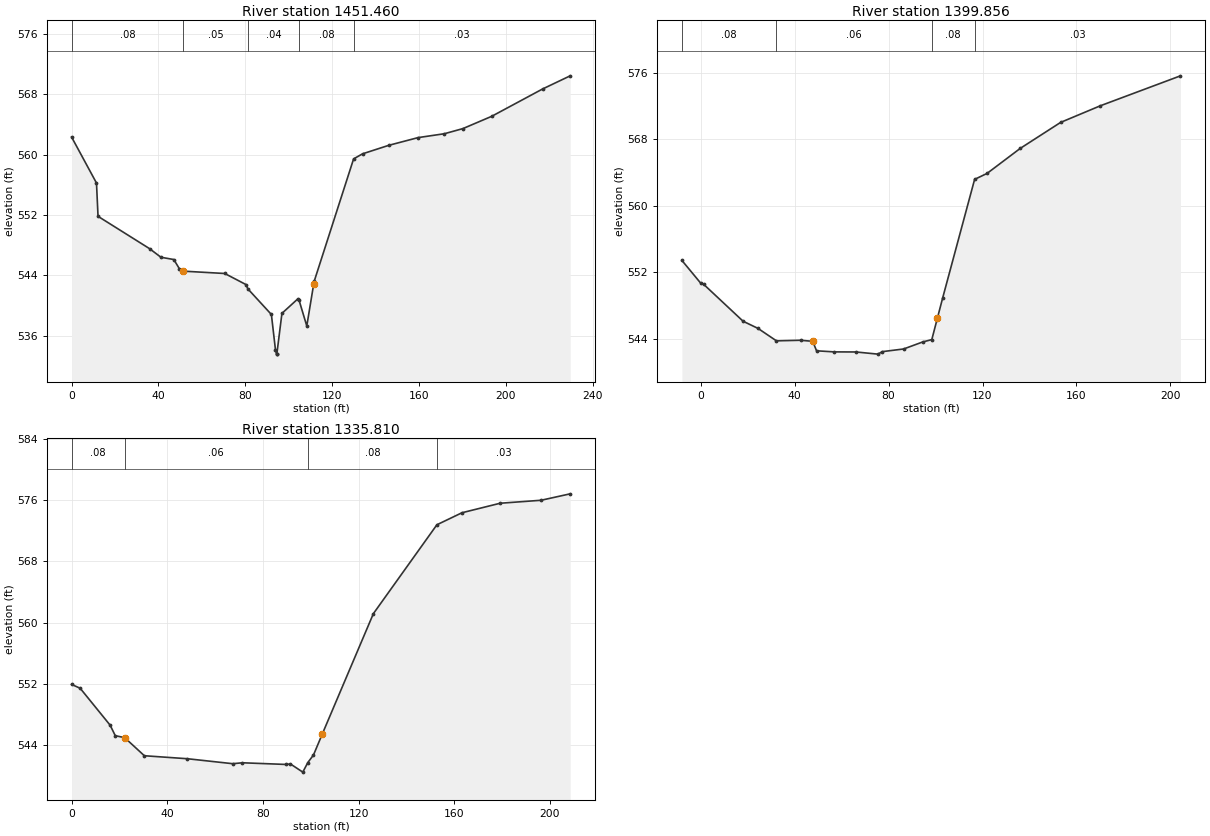
Type RM Length L Ch R = 1 ,1451.460,16.12,17.2,18.19
XS GIS Cut Line= 4
1355303.73138112 443907.866172251355305.41579066 443988.40334014
1355311.65637328 444041.995071051355279.93025453 444139.92744636
#Sta/Elev= 30
       0  562.31   11.47  556.22   12.18  551.81   35.92  547.53   41.16  546.39
   47.09  546.09   49.68  544.86   51.47  544.55   70.56  544.24   80.43  542.76
   81.16  542.22   92.05  538.81   93.94   534.1   94.43  533.56   94.59  533.64
   96.91  538.96  104.35  540.91  104.78  540.72  108.36  537.29  111.53  542.82
  111.84  543.27  129.93  559.42  134.05  560.09  146.18  561.22  159.68  562.24
  171.74  562.75  180.28  563.43   193.5  565.05  217.01  568.68  229.72  570.42
#Mann= 5 ,-1 , 0
       0     .08       0   51.47     .05       0   81.16     .04       0
  104.78     .08       0  129.93     .03       0
#XS Ineff= 2 , 0
Permanent Ineff=
       T       T
Bank Sta=51.47,111.53
XS Rating Curve= 0 ,0
Exp/Cntr=0.3,0.1

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
Type RM Length L Ch R = 1 ,1399.856,19.48,21.35,21.83
XS GIS Cut Line= 3
1355257.27477493 443927.108850051355254.70152583 444046.19417856
1355228.91576695 444127.38185349
#Sta/Elev= 24
   -8.01  553.43       0  550.69    1.34  550.53   18.06   546.1    24.4  545.24
   32.25  543.74   42.54  543.81    47.7  543.68   49.34  542.54   56.92  542.41
   66.07   542.4   75.46  542.14   77.34  542.44   86.41  542.76   94.48   543.6
   98.41  543.89  100.76  546.44  103.04  548.91  116.64  563.19  121.91   563.9
  136.07  566.92  153.26  570.05  170.24  572.06   204.3  575.66
#Mann= 4 ,-1 , 0
   -8.01     .08       0   32.25     .06       0   98.41     .08       0
  116.64     .03       0
Bank Sta=47.7,100.76
XS Rating Curve= 0 ,0
Exp/Cntr=0.3,0.1

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
Type RM Length L Ch R = 1 ,1335.810,0,0,0
XS GIS Cut Line= 3
1355209.68107387 443916.281233081355194.89294657 443962.34901434
1355181.96353082  444121.9369175
#Sta/Elev= 21
       0  551.92    3.58  551.42   16.11   546.6   18.26  545.23    22.2  544.97
   30.42  542.61   48.38  542.22   67.39  541.57   71.45  541.69   89.86  541.47
   91.49  541.54   96.68  540.47   98.76  541.71  101.15  542.71  104.78  545.41
  126.19  561.16  152.75  572.76  163.23  574.33  179.19  575.57  196.33  575.96
  208.49   576.8
#Mann= 4 ,-1 , 0
       0     .08       0    22.2     .06       0   98.76     .08       0
  152.75     .03       0
#XS Ineff= 2 , 0
Permanent Ineff=
       T       F
Bank Sta=22.2,104.78
XS Rating Curve= 0 ,0
Exp/Cntr=0.3,0.1
LCMann Table=0

Chan Stop Cuts=-1
Use User Specified Reach Order=0
Composite Channel Slope=5